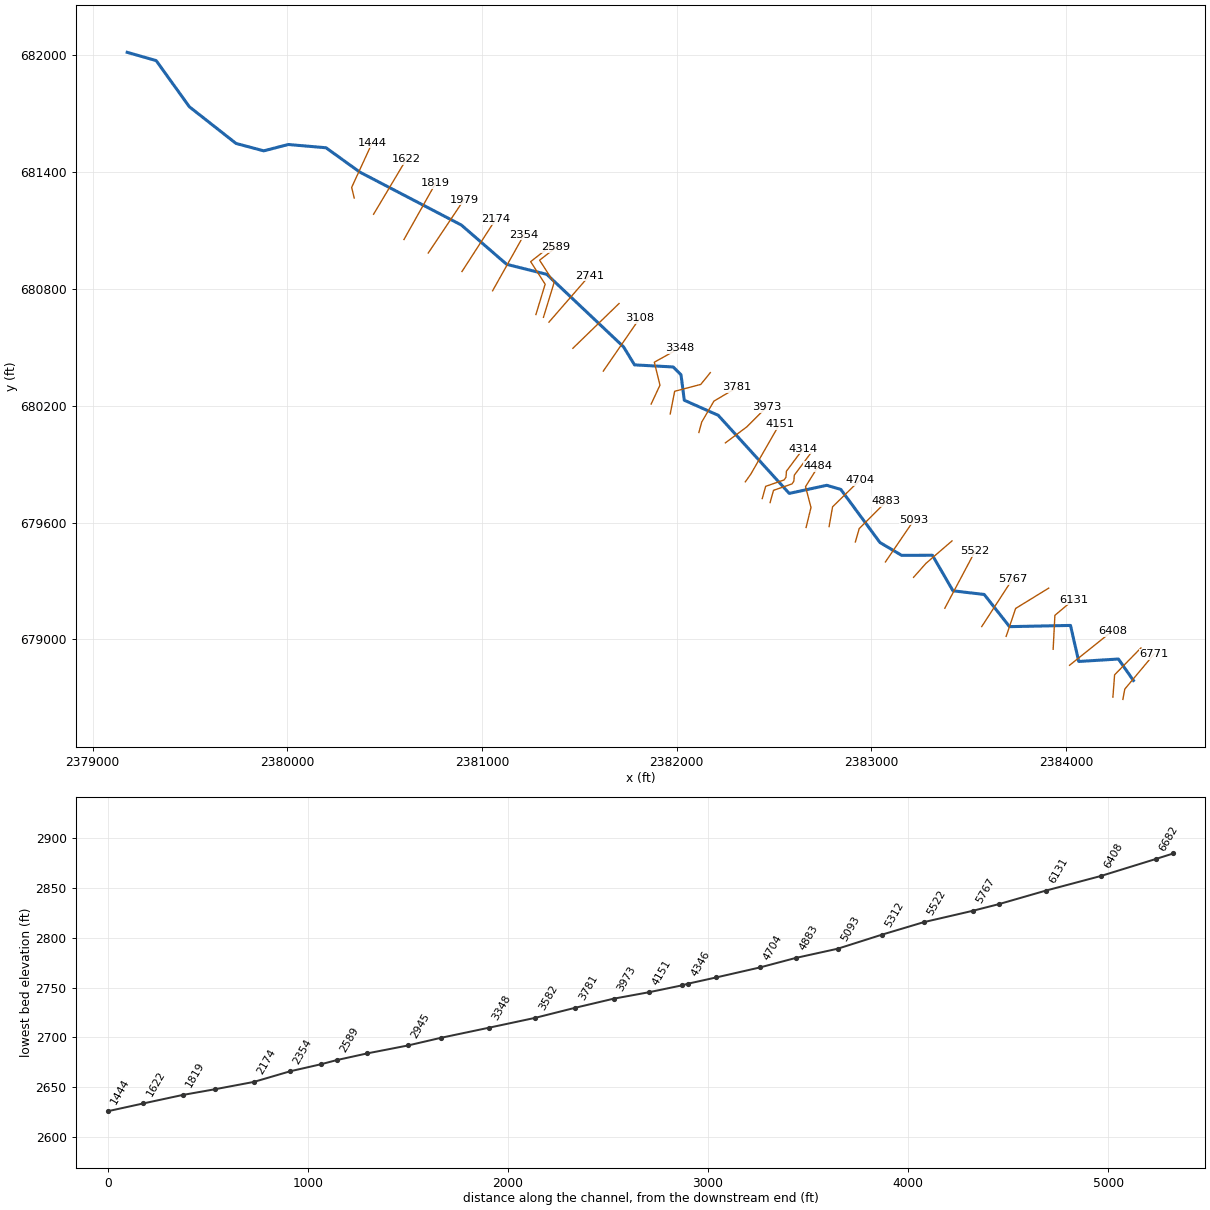
--- STNKGRN.prj (project) ---

Proj Title=STNKGRN
Current Plan=p01
Default Exp/Contr=0,0
English Units
Geom File=g01
Flow File=f01
Plan File=p01
BEGIN DESCRIPTION:
----------MODEL BY WOOD PLC 2022----------
AFH study
Randolph County, WV
HEC-RAS Version: RAS 6.2
Vertical Datum: NAVD88
Projection: NAD 1983 StatePlane West Virginia S FIPS 4702 (US Feet)
Terrain: 1-meter LIDAR (FEMA Region III 3DEP collected 2016-2018)
Land Use: 2019 NLCD
Hydrologic Method:
WV SIR2010-5033 regression equations
Additional Model Notes:
None
END DESCRIPTION:
DSS Export Rating Curves= 0
DSS Export Rating Curve Sorted= 0
DSS Export Volume Flow Curves= 0
DXF OffsetX= 0
DXF OffsetY= 0
DXF ScaleX= 0
DXF ScaleY= 0

--- STNKGRN.p01 (plan) ---

Plan Title=Floodplain
Program Version=6.20
Short Identifier=Floodplain
Geom File=g01
Flow File=f01
Subcritical Flow
K Sum by GR= 0
Std Step Tol= 0.01
Critical Tol= 0.01
Num of Std Step Trials= 20
Max Error Tol= 0.3
Flow Tol Ratio= 0.001
Split Flow NTrial= 30
Split Flow Tol= 0.02
Split Flow Ratio= 0.02
Log Output Level= 0
Friction Slope Method= 1
Unsteady Friction Slope Method= 2
Unsteady Bridges Friction Slope Method= 1
Parabolic Critical Depth
Global Vel Dist= 0 , 0 , 0
Global Log Level= 0
CheckData=True
Encroach Param=-1 ,0,0, 0
Mapping Interval=1HOUR
Computation Time Step Use Courant=        0
Computation Time Step Use Time Series=    0
Computation Time Step Count To Double=0
Computation Time Step Max Doubling=0
Computation Time Step Max Halving=0
Computation Time Step Residence Courant=0
Run HTab= 0
Run UNet= 0
Run Sediment= 0
Run PostProcess= 0
Run WQNet= 0
Run RASMapper=-1
UNET Theta= 0
UNET Theta Warmup= 0
UNET ZTol= 0
UNET ZSATol= 0
UNET MxIter= 0
UNET Max Iter WO Improvement= 0
UNET MaxInSteps= 0
UNET DtIC= 0
UNET DtMin= 0
UNET MaxCRTS= 0
UNET WFStab= 0
UNET SFStab= 0
UNET WFX= 1
UNET SFX= 1
UNET Gravity=32.174
UNET 1D Methodology=Finite Difference
UNET DSS MLevel= 1
UNET Pardiso=0
UNET DZMax Abort= 0
UNET Use Existing IB Tables= 0
UNET Froude Reduction=False
UNET Froude Limit= 0
UNET Froude Power= 0
UNET D1 Cores= 0
UNET WindReference=Eulerian
UNET WindDragFormulation=Hsu (1988)
UNET D2 Coriolis=0
UNET D2 Cores= 0
UNET D2 Theta= 1
UNET D2 Theta Warmup= 1
UNET D2 Z Tol= 0.01
UNET D2 Volume Tol= 0.01
UNET D2 Max Iterations= 20
UNET D2 Equation= 0
UNET D2 RampUpFraction=0.1
UNET D2 TimeSlices= 1
UNET D2 Turbulence Formulation=Non-Conservative (original)
UNET D2 Eddy Viscosity=0.3
UNET D2 Transverse Eddy Viscosity=0.1
UNET D2 Smagorinsky Mixing=0
UNET D2 BCVolumeCheck=0
UNET D2 Cores=0
UNET D2 SolverType=PARDISO (Direct)
UNET D2 Minimum Iterations= 2147483647
UNET D2 Maximum Iterations= 2147483647
UNET D2 Restart Number= 10
UNET D2 Relaxation Coeff=1.3
UNET D2 SOR Precondition Iterations= 10
UNET D2 ILUT Maximum Fill= 8
UNET D2 ILUT Tolerance=1E-08
UNET D1D2 MaxIter= 0
UNET D1D2 ZTol=0.01
UNET D1D2 QTol=0.1
UNET D1D2 MinQTol=1
Write IC File= 0
Write IC File at Fixed DateTime=0
Write IC File at Sim End=0
Echo Input=False
Echo Parameters=False
Echo Output=False
Write Detailed= 0
HDF Write Warmup=0
HDF Write Time Slices=0
HDF Flush=0
HDF Compression= 1
HDF Chunk Size= 1
HDF Spatial Parts= 1
HDF Use Max Rows=0
HDF Fixed Rows= 1
Calibration Method= 0
Calibration Iterations= 20
Calibration Max Change=0.05
Calibration Tolerance=0.2
Calibration Maximum=1.5
Calibration Minimum=0.5
Calibration Optimization Method= 1
WQ AD Non Conservative
WQ ULTIMATE=-1
WQ Max Comp Step=1HOUR
WQ Output Interval=15MIN
WQ Output Selected Increments= 0
WQ Output face flow=0
WQ Output face velocity=0
WQ Output face area=0
WQ Output face dispersion=0
WQ Output cell volume=0
WQ Output cell surface area=0
WQ Output cell continuity=0
WQ Output cumulative cell continuity=0
WQ Output face conc=0
WQ Output face dconc_dx=0
WQ Output face courant=0
WQ Output face peclet=0
WQ Output face adv mass=0
WQ Output face disp mass=0
WQ Output cell mass=0
WQ Output cell source sink temp=0
WQ Output nsm pathways=0
WQ Output nsm derived pathways=0
WQ Create Restart=0
WQ Fixed Restart=0
WQ System Summary=0
WQ Write To DSS=0
Sorting and Armoring Iterations= 10
XS Update Threshold= 0.02
Bed Roughness Predictor= 0
Hydraulics Update Threshold= 0.02
Energy Slope Method= 1
Volume Change Method= 1
Sediment Retention Method= 0
Sediment TS Multiplier= 1
Warm Up Method= 0
XS Weighting Method= 0
Number of US Weighted Cross Sections= 1
Number of DS Weighted Cross Sections= 1
Upstream XS Weight=0
Main XS Weight=1
Downstream XS Weight=0
Number of DS XS's Weighted with US Boundary= 1
Upstream Boundary Weight= 1
Weight of XSs Associated with US Boundary= 0
Number of US XS's Weighted with DS Boundary= 1
Downstream Boundary Weight= 0.5
Weight of XSs Associated with DS Boundary= 0.5
Percentile Method= 0
Sediment Output Level= 3
Mass or Volume Output= 0
Output Increment Type= 1
Profile and TS Output Increment= 1
Transport Output Increment 1
XS Output Flag= 0
XS Output Increment= 10
Read HDF5 Sediment Hotstart= 0
Sediment Hotstart Type= 0
Write Gradation File= 0
Read Gradation Hotstart= 0
Write HDF5 File= 1
Write Binary Output= 1
Write DSS Sediment File= 0
DSS Sediment Output Type= 1
SV Curve= 0
Specific Gage Flag= 0
Subcell Erosion Methods= 0
Subcell Deposition Methods= 0
Advection Scheme= 1
Matrix Solver= 0
Implicit Weighting Factor= 1
Maximum Outer Loop Convergence Iterations= 5
Convergence Maximum Absolute= 0.001
Convergence RMSE= 0.0001
Grain Fractions Max Abs Error= 0.001
Max Subgrid Regions= 1
Max Subgrid Length Scale= 3.402823E+38
Initial Layer Thickness= 3.402823E+38
Min Layer Thickness= 3.402823E+38
Max Layer Thickness= 3.402823E+38
Number of Layers= 5

--- STNKGRN.f01 (steady flow) ---

Flow Title=Flow
Program Version=6.20
Number of Profiles= 1
Profile Names=P100yr
River Rch & RM=STNKGRN,Main,6771
     372
River Rch & RM=STNKGRN,Main,4484
     426
River Rch & RM=STNKGRN,Main,3348
     484
Boundary for River Rch & Prof#=STNKGRN,Main            , 1
Up Type= 0
Dn Type= 3
Dn Slope=0.04379
DSS Import GetInterval= 0
DSS Import GetPeak= 0
DSS Import FillOption= 0

--- STNKGRN.g01 (geometry) ---

Geom Title=Geometry
Program Version=6.20

River Reach=STNKGRN         ,Main
Reach XY= 30
2384345.52300003678788.8799999952384268.46515722 678899.06444809
     2384064.707678886.5359999982384022.41995602679071.659318674
2383709.23800002679065.3560000062383579.23100001679230.668000013
2383418.70296448 679249.387860662383313.05800001679432.109000012
2383154.98500003      679431.588  2383043.539559679497.527346683
     2382842.745 679770.130000012382770.59299999679791.412000015
2382577.70114717679749.715030094 2382212.9068537680150.921344854
2382038.48300001680228.3069999962382021.81600003680359.035999998
2381981.97200003680399.141000003     2381783.134680409.908999994
2381726.49600004680502.6969999972381332.70024769680874.808830765
 2381126.2742708680926.3661562732380893.43100002681128.306999996
2380372.33700003681399.922000006     2380198.118681525.181999996
2380004.36900003681541.8490000072379878.58699998681509.297000021
2379736.13900003681547.3170000172379496.29499999681735.858999997
2379325.98300001681972.838000014      2379176.83      682015.466

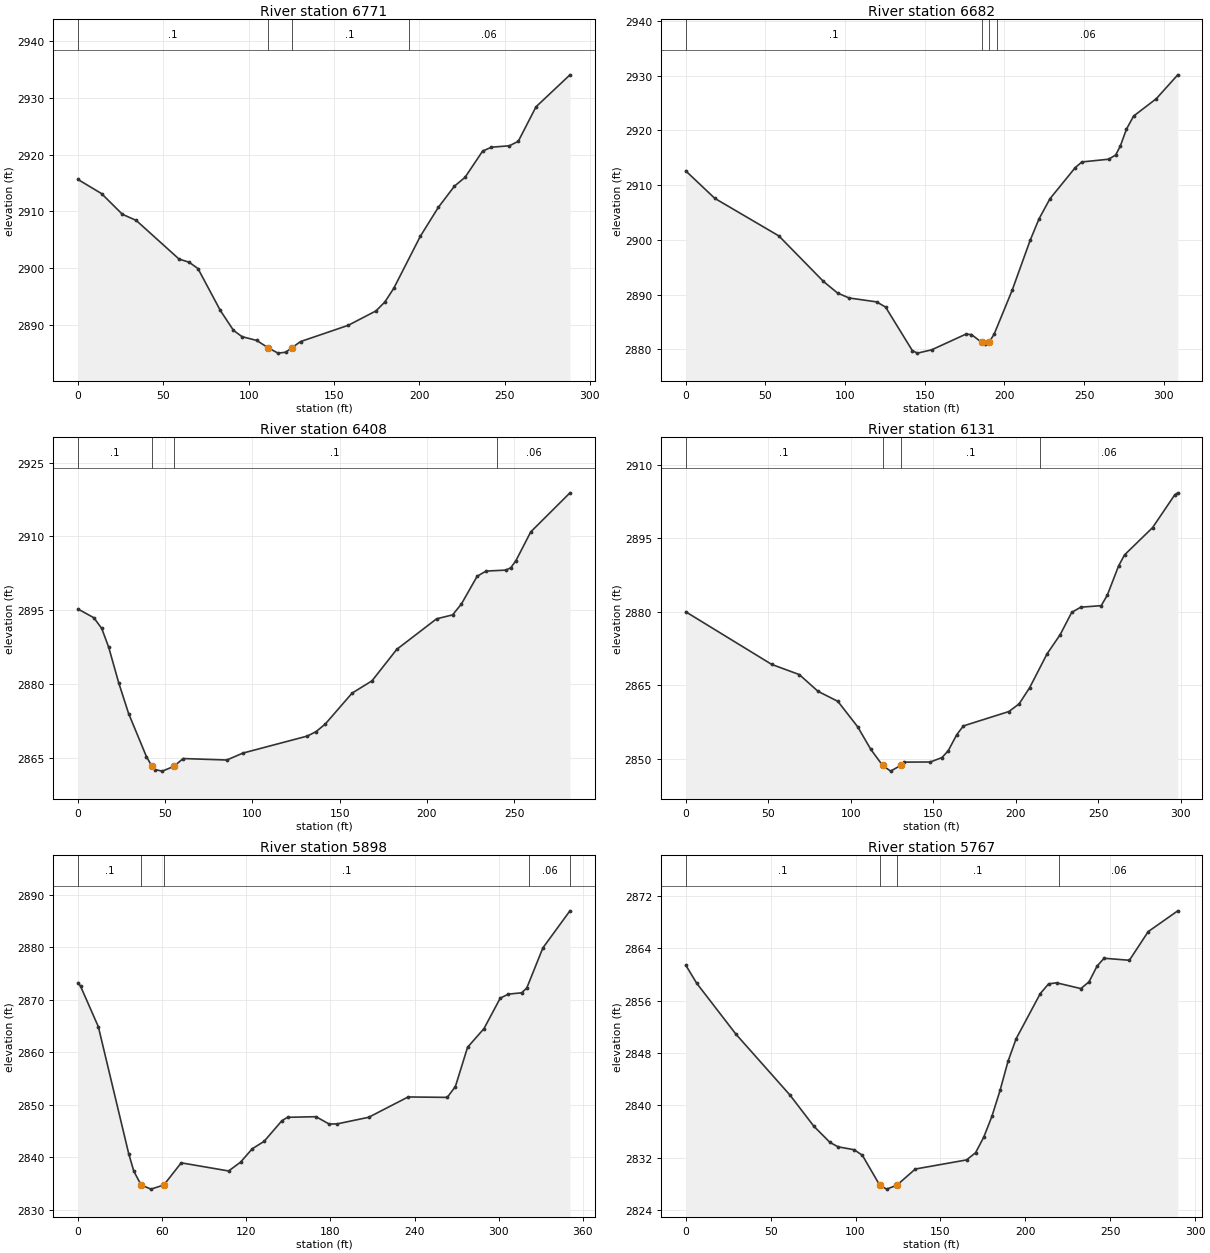
Type RM Length L Ch R = 1 ,6771    ,90,88.6,85.8
XS GIS Cut Line= 3
2384291.49265507678691.6341638492384301.11644148678744.482566207
 2384451.6196065678924.460199041
#Sta/Elev= 30
       0 2915.61    13.8 2913.12      26 2909.47    34.1 2908.39    59.2 2901.57
    65.1 2901.01    70.3 2899.89    83.4  2892.5    91.1 2888.99    96.1 2887.88
   104.7 2887.21  111.482885.901   117.2 2884.97   121.7 2885.13  125.262885.901
   130.4 2887.01   158.3 2889.87   174.6 2892.42   179.8 2893.99     185 2896.39
   200.6 2905.59   211.1 2910.67   220.6 2914.44   226.8 2915.99   237.1 2920.62
   242.3 2921.31   252.8 2921.56     258 2922.35   268.4 2928.44   288.3 2934.08
#Mann= 4, -1 ,  0
       0     0.1       0  111.48   0.045       0  125.26     0.1       0
  193.72    0.06       0
Bank Sta=111.48,125.26
XS Rating Curve= 0 ,0
Exp/Cntr(USF)=0,0
Exp/Cntr=0.3,0.1

Type RM Length L Ch R = 1 ,6682    ,277.1,274.4,268.9
XS GIS Cut Line= 3
2384240.19398454 678702.992554992384248.87737179678818.000895221
2384384.30021389678956.146598675
#Sta/Elev= 30
       0 2912.61    18.2  2907.6    58.4 2900.74    86.4 2892.42    95.3 2890.29
   102.5  2889.4   119.8 2888.68   125.4 2887.73   142.2 2879.78   145.4 2879.32
   154.3 2879.92   175.8 2882.79   179.3 2882.71  185.762881.282   187.8 2880.94
  190.342881.307   193.5 2882.76   204.8 2890.77   216.1  2899.9   221.7 2903.85
   228.6 2907.54   244.4  2913.2   248.6 2914.25   265.4 2914.75   269.8 2915.52
   272.7 2917.13   276.6 2920.25   281.1 2922.64   295.3  2925.8   308.8 2930.17
#Mann= 4, -1 ,  0
       0     0.1       0  185.76   0.045       0  190.34     0.1       0
  195.34    0.06       0
Bank Sta=185.76,190.34
XS Rating Curve= 0 ,0
Exp/Cntr(USF)=0,0
Exp/Cntr=0.3,0.1

Type RM Length L Ch R = 1 ,6408    ,270.1,276.4,279.3
XS GIS Cut Line= 2
2384017.58926553678866.9730456422384237.67615078679043.214061667
#Sta/Elev= 30
       0 2895.22     9.1 2893.44    13.6 2891.26    17.6 2887.43    23.3 2880.24
      29 2873.96    39.2 2865.21   42.422863.198    44.3 2862.54    48.3 2862.24
   54.872863.197    60.3  2864.8    85.3  2864.5    94.5 2865.91   131.5 2869.38
   136.5 2870.29   141.7 2871.81   157.1 2878.11   168.5 2880.61   182.7 2887.01
   205.5 2893.22   214.7 2894.03   219.7 2896.21   228.8 2901.89   233.9 2902.94
   245.3 2903.14   248.1 2903.64     251 2905.05   259.5 2910.91     282 2918.86
#Mann= 4, -1 ,  0
       0     0.1       0   42.42   0.045       0   54.87     0.1       0
     240    0.06       0
Bank Sta=42.42,54.87
XS Rating Curve= 0 ,0
Exp/Cntr(USF)=0,0
Exp/Cntr=0.3,0.1

Type RM Length L Ch R = 1 ,6131    ,235.2,233.2,230.4
XS GIS Cut Line= 3
2383933.27696536678949.1062603012383942.15682194679123.518227113
2384036.91573716679203.019350905
#Sta/Elev= 30
       0 2879.99    52.1 2869.25    68.8 2867.18    80.2 2863.75    92.2 2861.71
   104.2 2856.52   112.2 2851.89   119.32848.642   124.2 2847.46  130.372848.642
   132.4  2849.3   148.3 2849.33   155.3 2850.23   159.1 2851.61   164.3 2854.91
   168.3 2856.69   195.9 2859.63   202.1 2861.19   208.5 2864.51     219 2871.38
     227 2875.33     234 2879.88   239.5 2880.94   251.9 2881.25   255.6 2883.42
   262.4 2889.35     266 2891.61     283 2897.18   296.5  2903.9   298.3 2904.29
#Mann= 4, -1 ,  0
       0     0.1       0   119.3   0.045       0  130.37     0.1       0
  214.64    0.06       0
Bank Sta=119.3,130.37
XS Rating Curve= 0 ,0
Exp/Cntr(USF)=0,0
Exp/Cntr=0.3,0.1

Type RM Length L Ch R = 1 ,5898    ,134.4,130.8,127.7
XS GIS Cut Line= 3
2383691.90804536679015.4787066432383740.59336667679158.852059909
2383910.47493382679263.280729349
#Sta/Elev= 30
       0 2873.27     1.8 2872.61    14.5 2864.89    36.2 2840.65    39.8 2837.36
      452834.738      52 2833.95   61.192834.736    73.6 2838.96   107.4 2837.41
   115.9 2839.09   124.3 2841.65   132.7 2843.05   145.4 2846.99   149.4 2847.63
   169.7 2847.75   179.1 2846.35   184.8 2846.38   207.3 2847.64   235.4 2851.51
   263.3 2851.43   269.1 2853.49   277.8 2860.98   289.5 2864.53   301.1 2870.34
   306.9  2871.1   316.3 2871.35     320 2872.25   331.5 2879.91   350.8 2886.97
#Mann= 5, -1 ,  0
       0     0.1       0      45   0.045       0   61.19     0.1       0
  321.41    0.06       0  350.83     0.1       0
Bank Sta=45,61.19
XS Rating Curve= 0 ,0
Exp/Cntr(USF)=0,0
Exp/Cntr=0.3,0.1

Type RM Length L Ch R = 1 ,5767    ,244.9,244.9,244.9
XS GIS Cut Line= 2
2383566.58829513 679065.932266682383724.27643276679309.018784361
#Sta/Elev= 30
       0 2861.41     6.4 2858.66    29.5 2850.89    61.3  2841.6    75.4 2836.83
    84.9 2834.36    89.7 2833.68    99.2 2833.23     104 2832.39   114.2 2827.84
   118.3 2827.22  124.29 2827.81   135.2 2830.29   165.4 2831.68   170.7 2832.78
   175.5 2835.15   180.3 2838.32   185.1 2842.28   189.8 2846.73   194.6 2850.19
   208.8 2857.07   213.7 2858.56   218.4 2858.72   232.7 2857.84   237.5 2858.86
   242.3 2861.29   246.4 2862.47   261.3 2862.16   272.4 2866.54   289.8 2869.71
#Mann= 4, -1 ,  0
       0     0.1       0   114.2   0.045       0  124.29     0.1       0
     220    0.06       0
Bank Sta=114.2,124.29
XS Rating Curve= 0 ,0
Exp/Cntr(USF)=0,0
Exp/Cntr=0.3,0.1

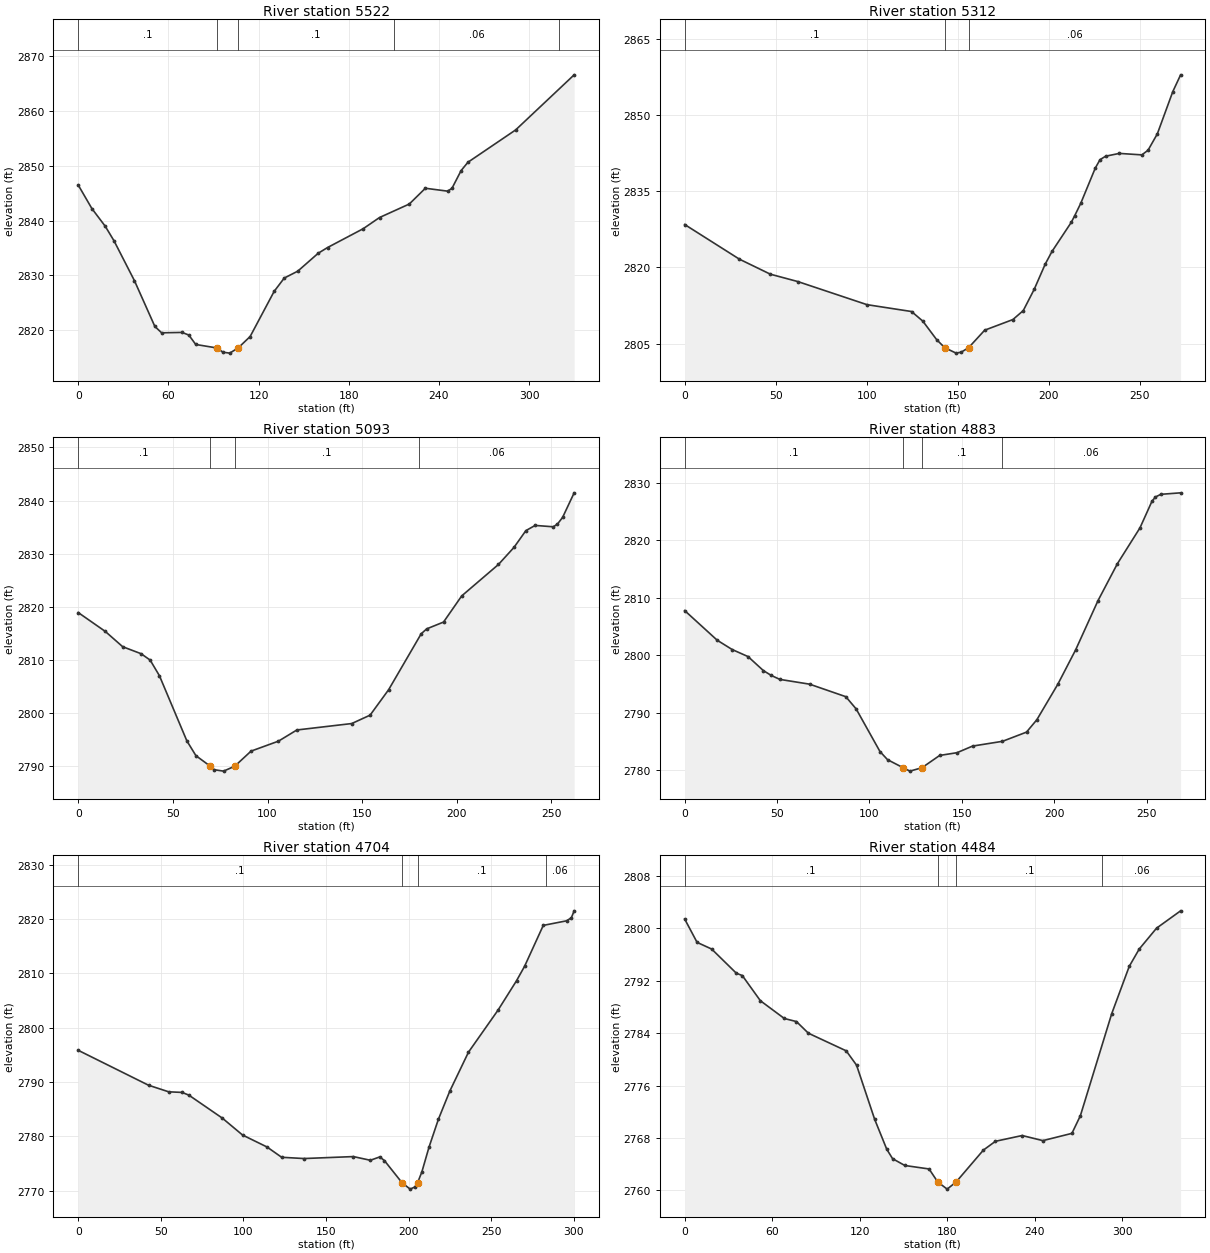
Type RM Length L Ch R = 1 ,5522    ,211.7,210,206.2
XS GIS Cut Line= 2
2383376.84661098 679160.143906942383531.66109861679451.575673258
#Sta/Elev= 30
       0 2846.49     9.1 2842.19      18 2838.96    23.8 2836.32    37.4 2829.04
      51 2820.68    55.5 2819.52    69.1 2819.59    73.6 2819.11    78.2 2817.39
   92.382816.749    96.3 2815.98   100.8 2815.81  106.392816.749   114.4 2818.84
   130.4 2827.09   137.1 2829.51   146.1 2830.77   159.7 2834.04   165.9 2835.08
   189.6 2838.51   200.5 2840.56   220.3 2843.02     231  2845.9   245.8 2845.37
   248.7 2845.89   254.8 2849.13   259.3 2850.64   291.1 2856.55     330  2866.6
#Mann= 5, -1 ,  0
       0     0.1       0   92.38   0.045       0  106.39     0.1       0
     210    0.06       0     320     0.1       0
Bank Sta=92.38,106.39
XS Rating Curve= 0 ,0
Exp/Cntr(USF)=0,0
Exp/Cntr=0.3,0.1

Type RM Length L Ch R = 1 ,5312    ,216,219.6,219.2
XS GIS Cut Line= 3
2383216.20716631679318.6573491472383279.64745701679390.128056394
 2383413.7554133679505.766054636
#Sta/Elev= 30
       0 2828.45    30.1 2821.63    47.1 2818.68    62.2 2817.23   100.2 2812.69
   124.7 2811.34   130.9 2809.45   138.5 2805.81  142.97 2804.22   149.2 2803.16
     152 2803.35  156.04 2804.22   164.9 2807.67   180.4 2809.76   186.1 2811.52
   192.1 2815.69   198.2 2820.68   201.9 2823.15   212.5 2828.88   214.4 2830.19
   217.7 2832.61   225.7 2839.55   228.3  2841.2   231.4 2841.88   238.9 2842.43
   251.3 2842.14   254.7 2843.06   259.8 2846.27   268.3 2854.58   272.6 2857.88
#Mann= 3, -1 ,  0
       0     0.1       0  142.97   0.045       0  156.04    0.06       0
Bank Sta=142.97,156.04
XS Rating Curve= 0 ,0
Exp/Cntr(USF)=0,0
Exp/Cntr=0.3,0.1

Type RM Length L Ch R = 1 ,5093    ,210.6,210,207.8
XS GIS Cut Line= 2
2383071.77458951679397.7482756392383219.35861075679614.239539224
#Sta/Elev= 30
       0 2818.95    14.3  2815.4    23.5 2812.52    33.2 2811.21      38 2810.01
    42.9 2807.07    57.4 2794.81    62.2 2792.02   69.772790.048    71.9 2789.38
    76.8 2789.12   82.71 2790.05    91.3 2792.88   105.8 2794.76   115.5 2796.86
   144.5 2798.07   154.2 2799.65     164 2804.44   181.2 2814.96   184.1 2815.88
     193 2817.16   202.6 2822.08     222 2827.99   230.2  2831.2   236.5 2834.36
   241.4 2835.34     251 2835.08   253.2  2835.6   255.9 2836.85     262 2841.47
#Mann= 4, -1 ,  0
       0     0.1       0   69.77   0.045       0   82.71     0.1       0
     180    0.06       0
Bank Sta=69.77,82.71
XS Rating Curve= 0 ,0
Exp/Cntr(USF)=0,0
Exp/Cntr=0.3,0.1

Type RM Length L Ch R = 1 ,4883    ,178.6,178.8,178.3
XS GIS Cut Line= 3
2382917.32643814679500.2563526172382937.14187036679569.009745437
2383076.40125562679708.193409235
#Sta/Elev= 30
       0 2807.77    17.6 2802.61    25.7 2800.99    34.3 2799.76    42.6 2797.32
    46.8 2796.49    51.5 2795.79    67.6 2794.96    87.2 2792.78    92.8 2790.65
   105.7 2783.23   109.8 2781.81  118.19 2780.42   121.9 2779.82   128.4 2780.41
     138 2782.55   147.4 2783.03   155.8 2784.18     172 2785.01     185 2786.61
   190.6 2788.77   201.9 2794.92   211.6 2800.94   223.7 2809.51   234.2 2815.94
   246.4 2822.17   252.9 2826.81   254.8 2827.55   257.7 2828.01   268.4 2828.27
#Mann= 4, -1 ,  0
       0     0.1       0  118.19   0.045       0   128.4     0.1       0
  171.55    0.06       0
Bank Sta=118.19,128.4
XS Rating Curve= 0 ,0
Exp/Cntr(USF)=0,0
Exp/Cntr=0.3,0.1

Type RM Length L Ch R = 1 ,4704    ,213.9,219.7,224.5
XS GIS Cut Line= 3
2382782.34106513 679579.20035835 2382800.2315893679680.829135308
2382941.19295223679818.662666809
#Sta/Elev= 30
       0 2795.83    42.6  2789.4    54.8 2788.19    62.9 2788.08      67 2787.58
    87.3 2783.34    99.5 2780.24   114.3 2778.04   123.2 2776.14   136.7 2775.91
   166.6 2776.27   176.9 2775.59   182.6 2776.21   185.4 2775.54  196.062771.465
     201 2770.28   203.8 2770.67  205.522771.467   208.1 2773.46   212.4 2777.99
   218.1 2783.14     225 2788.32   236.3 2795.48   254.2 2803.22   265.4 2808.63
   270.3  2811.3   281.6 2818.82   295.7 2819.66   298.6 2820.22   300.3  2821.5
#Mann= 4, -1 ,  0
       0     0.1       0  196.06   0.045       0  205.52     0.1       0
  283.19    0.06       0
Bank Sta=196.06,205.52
XS Rating Curve= 0 ,0
Exp/Cntr(USF)=0,0
Exp/Cntr=0.3,0.1

Type RM Length L Ch R = 1 ,4484    ,151.7,138.2,125.3
XS GIS Cut Line= 4
 2382664.2259201 679574.793974362382689.41184098679677.616968691
2382661.30538307679784.4215087342382726.82735916679889.236373927
#Sta/Elev= 30
       0 2801.44     8.5 2797.87    18.5 2796.85    35.4 2793.16    39.5  2792.8
    51.9 2788.95    68.3 2786.24    76.6 2785.77    84.8 2783.99   110.7  2781.3
   117.8 2779.11   130.2 2770.84   138.5 2766.26   142.5 2764.82   150.9 2763.78
   167.5 2763.25  173.442761.266   179.9 2760.17  186.052761.267   204.7 2766.13
     213 2767.48   231.3 2768.36   245.5 2767.58   265.4 2768.69   271.2 2771.39
   292.7 2786.99   304.7 2794.21   311.5 2796.84   323.4 2800.04   339.9 2802.69
#Mann= 4, -1 ,  0
       0     0.1       0  173.44   0.045       0  186.05     0.1       0
   286.3    0.06       0
Bank Sta=173.44,186.05
XS Rating Curve= 0 ,0
Exp/Cntr(USF)=0,0
Exp/Cntr=0.3,0.1

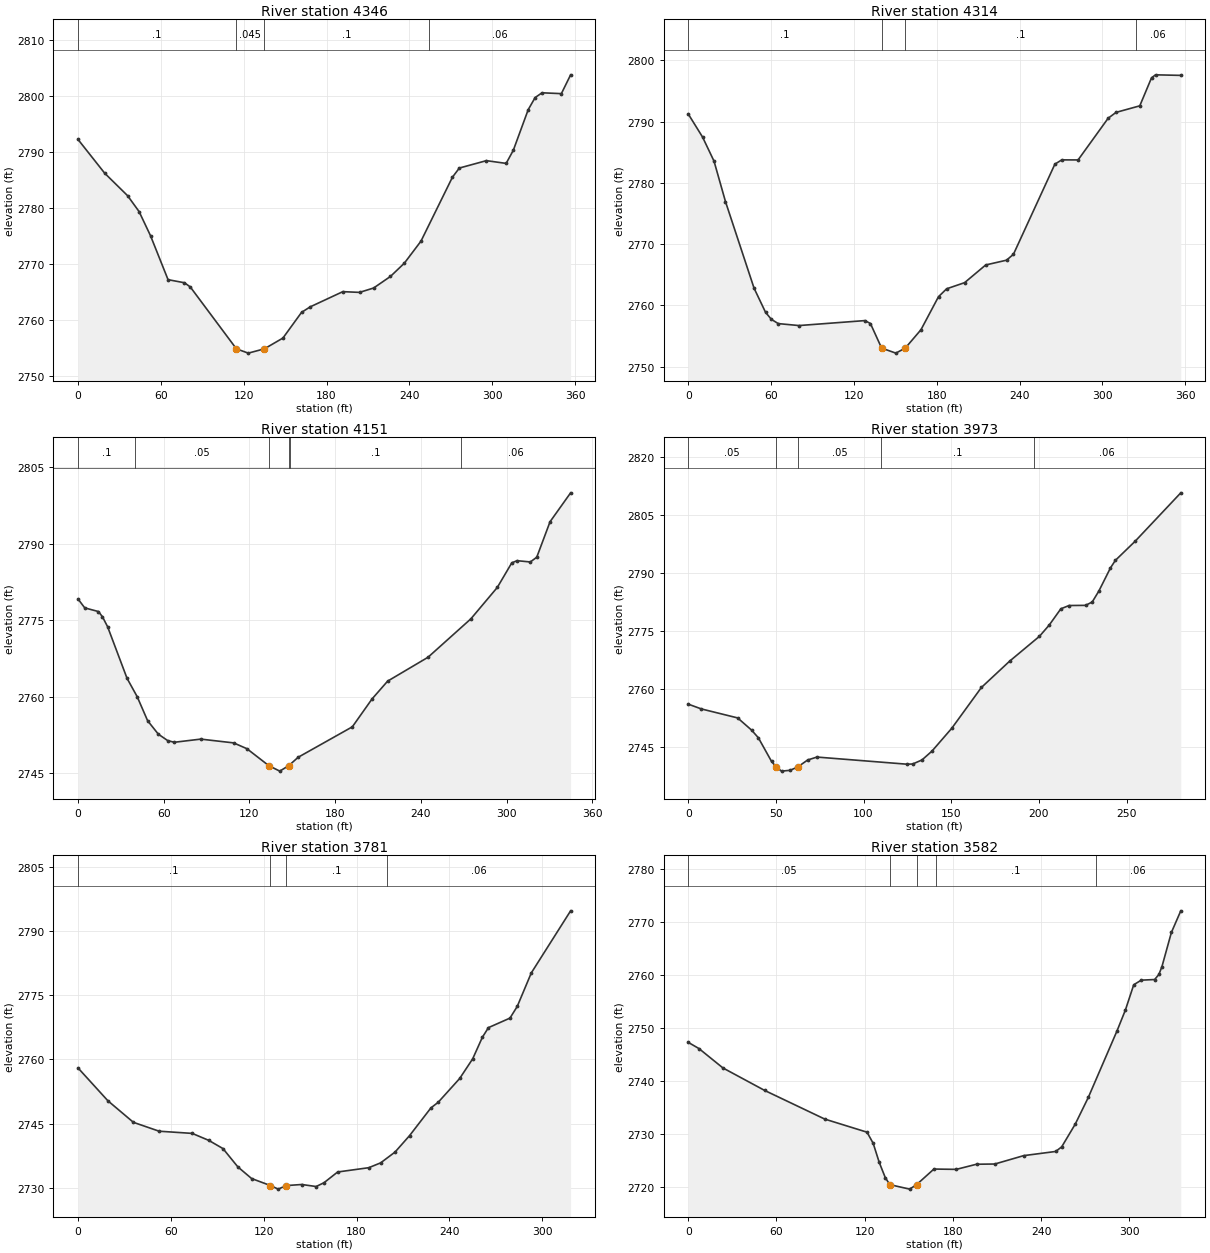
Type RM Length L Ch R = 1 ,4346    ,31.7,32.5,34.9
XS GIS Cut Line= 6
2382479.41161111679702.6244385872382496.88487823679765.474094468
2382591.64379346679798.3988023012382601.28029331679812.050510426
2382603.68941828 679843.369134952382689.01515738 679957.76532749
#Sta/Elev= 30
       0 2792.18    19.3 2786.16    35.9 2782.14    44.2 2779.31    52.5 2774.99
    65.2 2767.14    77.1 2766.59    81.3 2765.84  114.712754.787   123.3 2754.02
  134.972754.787   148.4 2756.71   161.9  2761.3   168.2 2762.29   191.8    2765
   203.9 2764.87   214.1 2765.65   226.3 2767.72   236.3 2770.07   248.4 2774.02
   271.2 2785.45   276.2 2787.08   295.8  2788.4   310.1 2787.91   315.3 2790.26
   326.1 2797.52   331.1 2799.67   336.1 2800.52   350.1 2800.37   356.8 2803.73
#Mann= 4, -1 ,  0
       0     0.1       0  114.71   0.045       0  134.97     0.1       0
   254.1    0.06       0
Bank Sta=114.71,134.97
XS Rating Curve= 0 ,0
Exp/Cntr(USF)=0,0
Exp/Cntr=0.3,0.1

Type RM Length L Ch R = 1 ,4314    ,157.8,163.1,167.7
XS GIS Cut Line= 6
2382439.05649406679723.1779361622382456.52976119679786.027592043
2382551.28867641679818.9522998762382560.92517627679832.604008002
2382563.33430123679863.9226325262382648.66004034679978.318825065
#Sta/Elev= 30
       0 2791.26    10.4 2787.48    18.7 2783.55      27 2776.95    47.7 2762.82
      56 2758.89    60.2 2757.74    65.2 2757.04    80.2 2756.72     128 2757.53
     132 2757.05   140.12753.042   150.4 2752.22  157.242753.042   168.6 2756.04
   181.3 2761.43   187.2 2762.72   200.2 2763.72   215.5 2766.61   230.6 2767.39
   235.6 2768.36   265.6 2783.06   270.6 2783.76   282.4 2783.75   304.2 2790.56
   309.9 2791.51   327.1 2792.58   335.6 2797.15   338.5 2797.64   356.8 2797.55
#Mann= 4, -1 ,  0
       0     0.1       0   140.1   0.045       0  157.24     0.1       0
   324.1    0.06       0
Bank Sta=140.1,157.24
XS Rating Curve= 0 ,0
Exp/Cntr(USF)=0,0
Exp/Cntr=0.3,0.1

Type RM Length L Ch R = 1 ,4151    ,179.6,177.8,174.2
XS GIS Cut Line= 3
2382352.13434611679809.3158000222382380.24080401679848.664841091
2382528.00046843680105.638170518
#Sta/Elev= 30
       0 2779.15     4.7 2777.41    14.3 2776.69    17.1 2775.66    20.7 2773.71
    34.3 2763.59    41.4 2759.99    48.7 2755.28    56.2 2752.64    62.8 2751.37
    67.4 2751.05    85.9 2751.67   108.9 2750.93   118.2 2749.79  133.532746.464
   141.2 2745.39  147.482746.462   154.1 2748.11     192 2754.08   205.8 2759.55
   216.7 2763.04     245 2767.73     275 2775.27   293.5 2781.43   303.6 2786.24
   307.3 2786.67   316.6 2786.42   321.1 2787.35   330.4 2794.31   344.8 2799.98
#Mann= 6, -1 ,  0
       0     0.1       0      40    0.05       0  133.53   0.045       0
  147.48    0.05       0  148.36     0.1       0  268.36    0.06       0
Bank Sta=133.53,147.48
XS Rating Curve= 0 ,0
Exp/Cntr(USF)=0,0
Exp/Cntr=0.3,0.1

Type RM Length L Ch R = 1 ,3973    ,189.8,191.8,194.1
XS GIS Cut Line= 3
  2382249.617818680009.233219578  2382359.361721680091.183420738
2382461.24873839680192.796788941
#Sta/Elev= 30
       0 2756.14     7.5  2754.9    28.2 2752.58    36.1 2749.45      40 2747.46
    47.5 2741.37   50.182739.926    53.2 2738.85    58.1 2739.06   62.462739.928
    68.1 2741.72    73.4 2742.48   124.7 2740.64     128 2740.69   133.3 2741.73
     139 2744.01   150.3 2749.91   167.2 2760.44   183.3 2767.23   200.3 2773.64
   205.9 2776.56   212.5 2780.74   217.2 2781.59   226.6 2781.63   230.4  2782.5
   234.2 2785.34   240.8  2791.3   243.6 2793.24   254.9 2798.19   280.9 2810.67
#Mann= 5, -1 ,  0
       0    0.05       0   50.18   0.045       0   62.46    0.05       0
     110     0.1       0  196.97    0.06       0
Bank Sta=50.18,62.46
XS Rating Curve= 0 ,0
Exp/Cntr(USF)=0,0
Exp/Cntr=0.3,0.1

Type RM Length L Ch R = 1 ,3781    ,205.8,199.2,191.8
XS GIS Cut Line= 4
2382113.61776934 680062.576952872382128.08572451680116.077712026
2382190.72297356680223.6852937242382309.88830727680294.228442473
#Sta/Elev= 30
       0 2758.01    19.3 2750.35    35.8 2745.32    52.4 2743.25    73.8 2742.74
    84.5 2741.11    93.7 2739.19   103.3 2734.92   112.2  2732.2   124.32730.574
   129.4 2729.73  134.57 2730.56   144.6 2730.81   153.9 2730.34     159 2731.23
   167.8 2733.73   187.9 2734.73   195.6 2735.86   204.9 2738.38   214.3 2742.22
   228.1 2748.69   232.8    2750   246.7 2755.56   255.1 2760.15   261.4 2765.21
   265.3 2767.43   279.2 2769.65   283.9 2772.38     293 2780.21   318.4 2794.69
#Mann= 4, -1 ,  0
       0     0.1       0   124.3   0.045       0  134.57     0.1       0
  199.93    0.06       0
Bank Sta=124.3,134.57
XS Rating Curve= 0 ,0
Exp/Cntr(USF)=0,0
Exp/Cntr=0.3,0.1

Type RM Length L Ch R = 1 ,3582    ,219.3,233.8,243.8
XS GIS Cut Line= 4
 2381966.4110692680157.9774929542381989.15951829680274.276917955
2382123.26747458680309.6107507512382172.28748581680370.103014528
#Sta/Elev= 30
       0 2747.34     7.3 2746.17    23.6 2742.51      52 2738.26    92.9 2732.85
   121.6 2730.38   125.8 2728.28   129.9 2724.69     134 2721.82  137.112720.478
   150.6 2719.63  155.322720.478   167.1 2723.42   182.3 2723.36   196.1 2724.33
   208.5 2724.37   228.1 2725.95   249.9 2726.74     254 2727.61   263.2 2731.89
   272.1 2736.94   291.7 2749.55   297.3 2753.42     303 2758.21   308.1 2759.08
   317.2  2759.2   320.1 2760.15   322.2 2761.65   328.6 2768.08     335 2772.17
#Mann= 5, -1 ,  0
       0    0.05       0  137.11   0.045       0  155.32    0.05       0
   168.5     0.1       0  277.19    0.06       0
Bank Sta=137.11,155.32
XS Rating Curve= 0 ,0
Exp/Cntr(USF)=0,0
Exp/Cntr=0.3,0.1

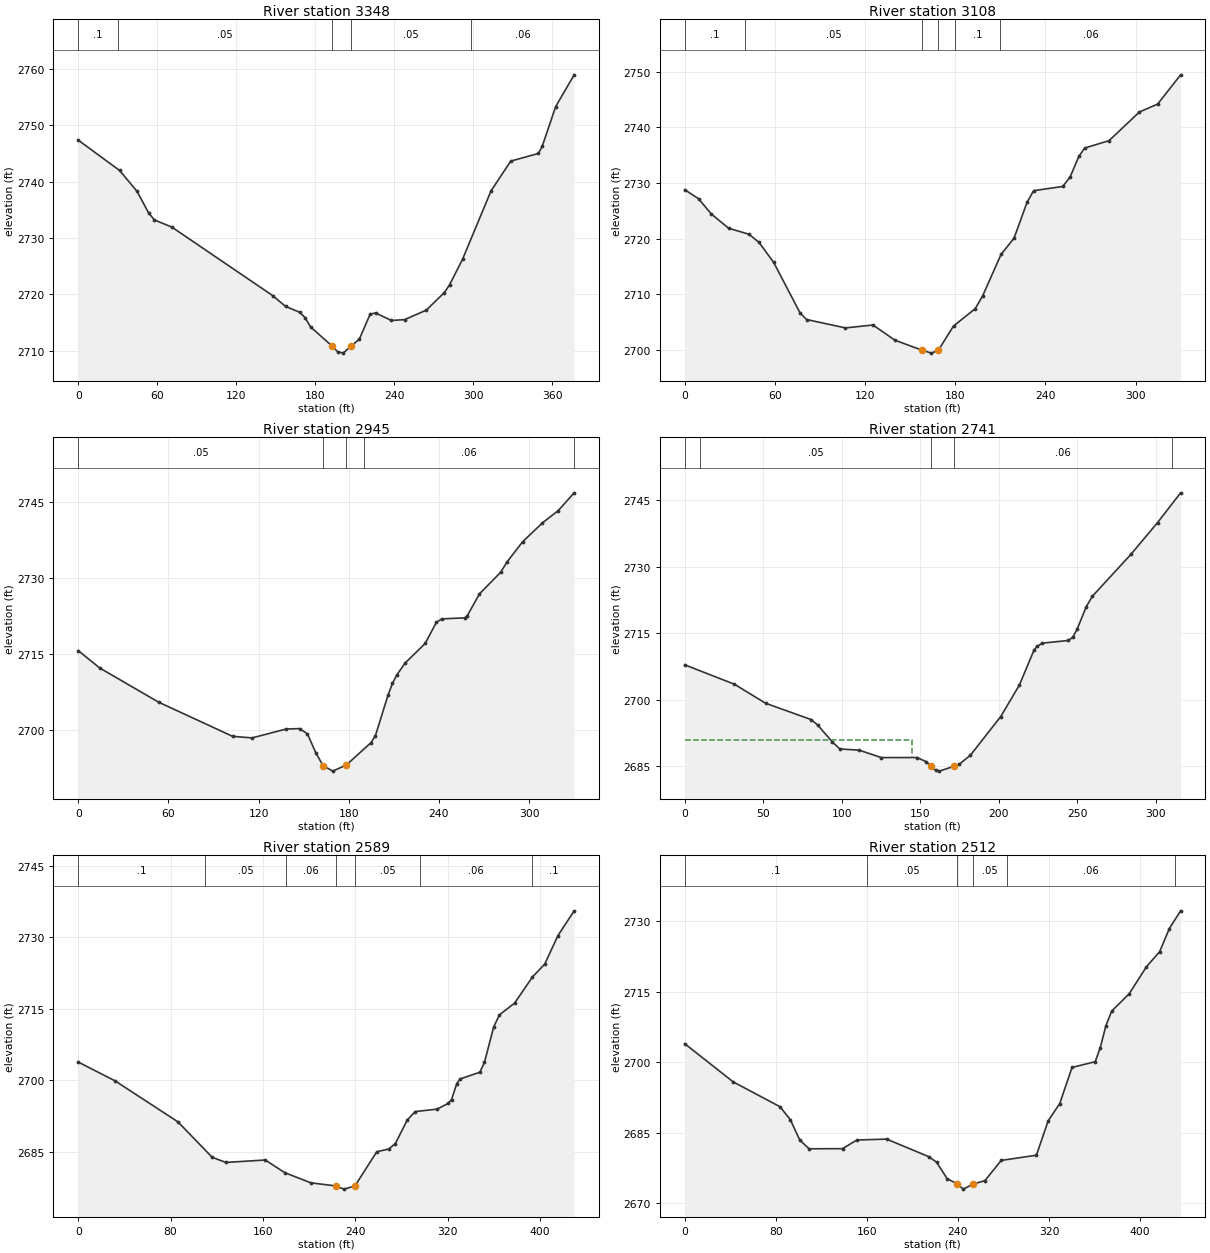
Type RM Length L Ch R = 1 ,3348    ,246.4,240.1,234.3
XS GIS Cut Line= 4
 2381868.3831894680208.7168867122381913.67360277680305.595542479
2381884.76410321680423.6426656852382014.25701255 680495.99116593
#Sta/Elev= 30
       0 2747.36    31.4 2741.99    44.7 2738.28    53.5 2734.45    57.9 2733.21
    71.2 2731.93   147.7  2719.8   157.5 2717.88   168.3 2716.83   172.4 2715.88
   176.5 2714.24  193.062710.814   197.1 2709.85   201.2 2709.59   207.32710.814
   213.6 2712.08   221.8  2716.5   225.9 2716.72     238 2715.38     248 2715.53
   264.5 2717.22   278.2 2720.34   282.1 2721.68     292 2726.23   313.6 2738.34
   328.6 2743.64   349.7    2745   352.6 2746.31   362.8 2753.32   376.8 2758.94
#Mann= 5, -1 ,  0
       0     0.1       0      30    0.05       0  193.06   0.045       0
   207.3    0.05       0  298.48    0.06       0
Bank Sta=193.06,207.3
XS Rating Curve= 0 ,0
Exp/Cntr(USF)=0,0
Exp/Cntr=0.3,0.1

Type RM Length L Ch R = 1 ,3108    ,164,162.7,161.2
XS GIS Cut Line= 2
 2381622.5950967680377.9630494662381809.77039809680649.744959365
#Sta/Elev= 30
       0 2728.79     9.2 2727.17    17.8  2724.4    29.3 2721.86    42.8 2720.78
    49.5 2719.31    59.2 2715.73    76.8 2706.64    81.1 2705.47     107 2703.96
   125.3 2704.48   139.9 2701.75   157.9 2699.96   164.2 2699.43   168.8 2699.96
   178.9  2704.3   193.3 2707.41   198.2 2709.68   210.5 2717.15   219.2  2720.1
   227.8 2726.51   232.2 2728.61   251.6 2729.37   256.5 2731.09   262.3 2734.78
   266.2 2736.27   282.4  2737.6   302.6 2742.75   314.7 2744.16     330 2749.42
#Mann= 6, -1 ,  0
       0     0.1       0      40    0.05       0   157.9   0.045       0
   168.8    0.05       0     180     0.1       0     210    0.06       0
Bank Sta=157.9,168.8
XS Rating Curve= 0 ,0
Exp/Cntr(USF)=0,0
Exp/Cntr=0.3,0.1

Type RM Length L Ch R = 1 ,2945    ,203.2,204.3,204.3
XS GIS Cut Line= 2
2381466.47595903680495.2479674522381703.33261162680725.028136571
#Sta/Elev= 30
       0 2715.68    14.3 2712.24    53.5 2705.47   102.7 2698.71   115.7  2698.4
   138.3 2700.15   147.3 2700.24   152.5 2699.21   158.1 2695.45   162.9 2692.92
   169.4 2691.82   178.52693.051   194.9 2697.48   197.8 2698.87   206.2 2706.92
   209.1 2709.17   211.9 2710.82   217.6 2713.24   230.9  2717.1   238.3 2721.27
     242 2721.96   257.2 2722.16   258.7 2722.49     267 2726.91     281 2731.15
   285.4 2733.25   295.7 2737.22   308.9 2740.96   319.4 2743.39     330 2746.91
#Mann= 5, -1 ,  0
       0    0.05       0   162.9   0.045       0   178.5    0.05       0
     190    0.06       0     330     0.1       0
Bank Sta=162.9,178.5
XS Rating Curve= 0 ,0
Exp/Cntr(USF)=0,0
Exp/Cntr=0.3,0.1

Type RM Length L Ch R = 1 ,2741    ,152.1,152,166.8
XS GIS Cut Line= 2
 2381343.3592787680629.3742422682381550.56698921 680867.59699608
#Sta/Elev= 30
       0 2707.85    31.7 2703.45    51.5 2699.16    80.5 2695.47    84.6 2694.27
      94 2690.41    98.8 2688.82     111 2688.57   125.2 2686.88   147.9 2686.89
   153.6 2685.98  156.822684.924   159.7 2684.01   162.1 2683.82  171.512684.923
   174.7 2685.35   181.9 2687.42   201.2 2696.16   213.1  2703.3   222.4  2711.2
   224.4 2712.03   227.7 2712.74   244.3 2713.35   247.1 2714.12   249.9 2715.95
   255.6 2720.97   259.5 2723.33     284 2732.78     301 2739.98   315.7 2746.71
#Mann= 5, -1 ,  0
       0     0.1       0      10    0.05       0  156.82   0.045       0
  171.51    0.06       0     310     0.1       0
#XS Ineff= 2 , 0
          144.39 2690.92
Permanent Ineff=
       F       F
Bank Sta=156.82,171.51
XS Rating Curve= 0 ,0
Exp/Cntr(USF)=0,0
Exp/Cntr=0.3,0.1

Type RM Length L Ch R = 1 ,2589    ,72.4,76.8,69.8
XS GIS Cut Line= 4
2381315.20702235680654.2404399592381369.80820002680832.017863497
2381295.36623865 680947.655861742381379.21467191 681012.87011645
#Sta/Elev= 30
       0  2703.8    31.9 2699.85    86.4 2691.24   116.1 2683.78     128 2682.71
   162.1 2683.22   178.8 2680.58   201.6 2678.42  223.24 2677.77   230.2  2677.1
   239.7 2677.75   258.7 2684.96     269 2685.52   274.8 2686.68   285.1 2691.63
     292 2693.39     311 2693.91   320.6 2695.12   323.5 2695.93     328 2699.27
   330.9 2700.25     348 2701.66     352 2703.75     360 2711.19     365 2713.73
   378.1 2716.18   393.6 2721.68   404.2 2724.38   415.7 2730.38   429.7 2735.57
#Mann= 7, -1 ,  0
       0     0.1       0     110    0.05       0     180    0.06       0
  223.24   0.045       0   239.7    0.05       0  295.97    0.06       0
   393.5     0.1       0
Bank Sta=223.24,239.7
XS Rating Curve= 0 ,0
Exp/Cntr(USF)=0,0
Exp/Cntr=0.3,0.1

Type RM Length L Ch R = 1 ,2512    ,164,157.6,150.1
XS GIS Cut Line= 4
2381276.54600895680668.4257607242381323.91981173680824.521059592
2381249.47785037680940.1590578342381355.73114578681023.441749769
#Sta/Elev= 30
       0 2703.96    42.6 2695.84    83.7 2690.55    92.8 2687.81   101.1 2683.47
   109.3  2681.6   138.7 2681.63   151.3 2683.47   177.4 2683.66   214.4 2679.93
   221.3 2678.75   230.5 2675.28  239.34 2674.11   244.8 2673.02   253.1 2674.06
   263.8 2674.84   278.1 2679.13     309 2680.23   319.3 2687.53   329.5 2691.22
   340.3 2698.91   360.7 2700.13   365.1 2703.13   370.1 2707.81   375.2 2710.91
   390.5 2714.57   405.7 2720.33   417.3 2723.54   425.8 2728.46   435.7 2732.22
#Mann= 6, -1 ,  0
       0     0.1       0     160    0.05       0  239.34   0.045       0
   253.1    0.05       0  283.13    0.06       0  430.65     0.1       0
Bank Sta=239.34,253.1
XS Rating Curve= 0 ,0
Exp/Cntr(USF)=0,0
Exp/Cntr=0.3,0.1

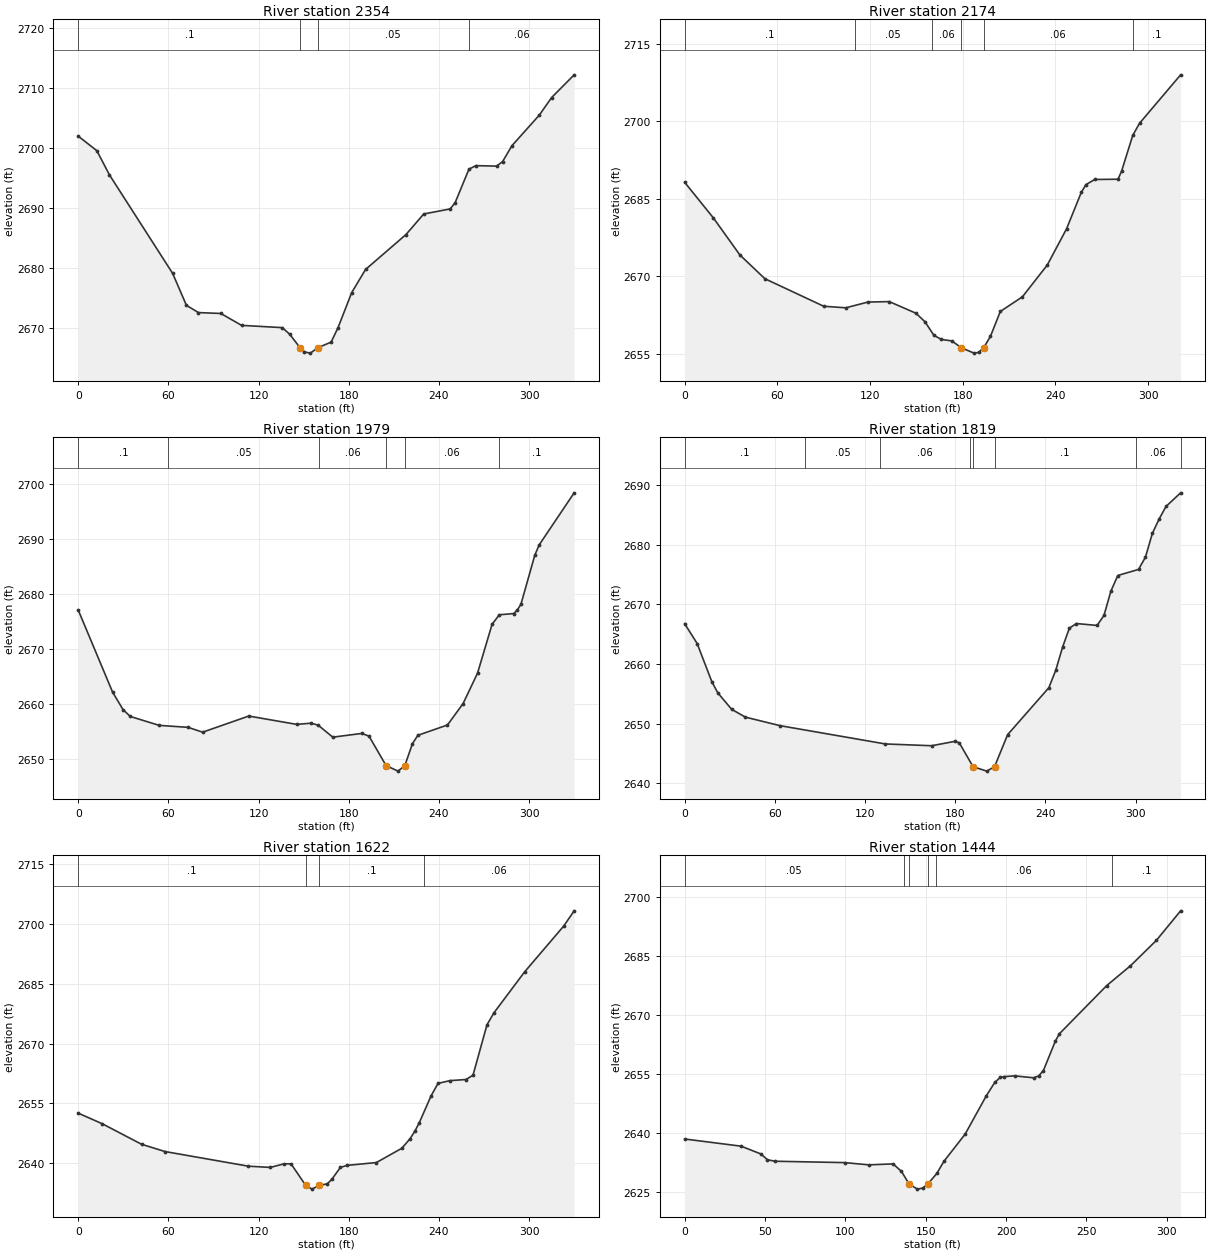
Type RM Length L Ch R = 1 ,2354    ,180.8,180.9,180.6
XS GIS Cut Line= 2
2381053.98409808680790.4309346652381215.49361923681078.206323779
#Sta/Elev= 30
       0 2701.94    12.4 2699.51    20.8 2695.47    62.8 2679.07      72 2673.73
      80 2672.52    94.9 2672.37   108.7 2670.39   135.8 2670.01   140.8 2668.89
  147.88 2666.57   150.5 2665.95   154.5 2665.76   159.3 2666.64   168.3  2667.6
   172.9 2670.02     182 2675.86   191.2 2679.71   218.1 2685.53   229.9 2688.96
   247.5  2689.8   250.8 2690.84     260 2696.43   264.6 2697.02   278.4 2696.94
   282.4  2697.7   288.6 2700.34   306.9 2705.47     315 2708.37     330 2712.16
#Mann= 4, -1 ,  0
       0     0.1       0  147.88   0.045       0   159.3    0.05       0
     260    0.06       0
Bank Sta=147.88,159.3
XS Rating Curve= 0 ,0
Exp/Cntr(USF)=0,0
Exp/Cntr=0.3,0.1

Type RM Length L Ch R = 1 ,2174    ,195.4,195.1,194.9
XS GIS Cut Line= 2
2380896.78195573680889.5674336032381070.96169058681159.148517005
#Sta/Elev= 30
       0 2688.15    18.6 2681.25    35.7 2674.11    51.9  2669.5      90 2664.17
   104.3 2663.87   118.6 2664.98   132.4 2665.07   149.7 2662.82   155.5 2661.18
   161.3 2658.55   166.2 2657.74   172.9 2657.47  179.072656.137   187.3  2655.1
   190.2 2655.23  193.532656.136   197.9 2658.34   204.3 2663.16   218.6    2666
   234.7 2672.15   247.2 2679.17   256.7  2686.2   259.7  2687.7   265.4  2688.7
   280.5 2688.75   282.8 2690.32     290 2697.22   294.4 2699.57     321 2708.95
#Mann= 6, -1 ,  0
       0     0.1       0     110    0.05       0     160    0.06       0
  179.07   0.045       0  193.53    0.06       0     290     0.1       0
Bank Sta=179.07,193.53
XS Rating Curve= 0 ,0
Exp/Cntr(USF)=0,0
Exp/Cntr=0.3,0.1

Type RM Length L Ch R = 1 ,1979    ,160,159.9,160.8
XS GIS Cut Line= 2
2380723.44583198680984.4016639812380907.09996406681258.575258202
#Sta/Elev= 30
       0 2677.08    22.9 2662.09    29.8 2658.94    34.6 2657.68    53.9 2656.05
    73.1 2655.69    82.8 2654.81   113.5 2657.75   145.4 2656.23     155 2656.45
   159.7 2656.08   169.4  2653.9   188.7 2654.58   193.5 2654.09  204.86 2648.72
   212.8 2647.71   217.3  2648.7   222.4 2652.71     226 2654.24   245.7 2656.12
   256.1 2660.03   265.7 2665.56   275.4 2674.48   280.2 2676.21   289.8 2676.43
   292.3 2677.12   294.6 2678.14   303.8 2687.06   306.7 2688.94     330 2698.44
#Mann= 6, -1 ,  0
       0     0.1       0      60    0.05       0     160    0.06       0
  204.86   0.045       0   217.3    0.06       0     280     0.1       0
Bank Sta=204.86,217.3
XS Rating Curve= 0 ,0
Exp/Cntr(USF)=0,0
Exp/Cntr=0.3,0.1

Type RM Length L Ch R = 1 ,1819    ,196.9,197.1,196.9
XS GIS Cut Line= 2
2380598.77024403681053.9321076192380760.45668607681341.608131057
#Sta/Elev= 30
       0 2666.74     8.3 2663.42    18.1 2656.99    22.1 2655.12    31.3 2652.37
    40.4 2651.07    63.4 2649.64   133.5 2646.57   164.3 2646.27   179.7    2647
   182.7 2646.77   191.9 2642.75     201 2642.01  206.17 2642.75   214.9 2648.13
   242.3    2656   246.9 2658.92   251.5 2662.85     256 2666.01   260.7 2666.77
   274.4 2666.45     279 2668.13   283.6 2672.21   288.2 2674.83     302 2675.85
   306.6 2677.91   311.2  2681.9   315.7 2684.31   320.3 2686.42     330  2688.7
#Mann= 8, -1 ,  0
       0     0.1       0      80    0.05       0     130    0.06       0
     190     0.1       0   191.9   0.045       0  206.17     0.1       0
     300    0.06       0     330     0.1       0
Bank Sta=191.9,206.17
XS Rating Curve= 0 ,0
Exp/Cntr(USF)=0,0
Exp/Cntr=0.3,0.1

Type RM Length L Ch R = 1 ,1622    ,176.6,177.3,177.8
XS GIS Cut Line= 2
2380442.58642693681183.5308868872380611.56914054681466.982545022
#Sta/Elev= 30
       0 2652.55    15.9 2649.91    42.2 2644.73    57.8 2642.91   113.2 2639.24
   127.8 2638.93     137 2639.83   141.6 2639.83  151.38 2634.42   155.6 2633.48
   160.3 2634.43   165.7  2634.8   168.7 2635.92   174.5 2638.95   178.9 2639.44
   198.4 2640.15   215.3 2643.73   220.8 2646.12   224.1 2648.08     227 2650.19
   234.8 2656.89   239.4 2660.02   247.4 2660.71     258 2660.99   262.7 2662.08
     272 2674.73   276.6 2677.72     297 2687.99   323.1 2699.53     330 2703.33
#Mann= 4, -1 ,  0
       0     0.1       0  151.38   0.045       0   160.3     0.1       0
     230    0.06       0
Bank Sta=151.38,160.3
XS Rating Curve= 0 ,0
Exp/Cntr(USF)=0,0
Exp/Cntr=0.3,0.1

Type RM Length L Ch R = 1 ,1444    ,160.7,163.6,169
XS GIS Cut Line= 3
2380343.18731106681267.088054781 2380330.0663826681321.708880217
  2380435.771183681550.898180767
#Sta/Elev= 30
       0 2638.43    35.1  2636.6    47.4 2634.62    51.5 2633.14    56.2 2632.76
    99.6 2632.41   114.6 2631.84   129.7 2632.08   134.9 2630.17  139.692626.925
   144.8 2625.65   148.1 2625.92  151.242626.922   156.9 2629.65   161.3 2632.73
   174.5 2639.66   187.7 2649.45     193 2652.87   196.5 2654.19     199 2654.34
   205.4 2654.52   217.1 2654.04   220.2 2654.49   223.2 2655.87   230.6 2663.33
   233.1 2665.23   262.6 2677.54   277.4 2682.59   293.5 2689.06   308.6  2696.6
#Mann= 6, -1 ,  0
       0    0.05       0  136.17     0.1       0  139.69   0.045       0
  151.24     0.1       0  156.17    0.06       0  266.17     0.1       0
Bank Sta=139.69,151.24
XS Rating Curve= 0 ,0
Exp/Cntr(USF)=0,0
Exp/Cntr=0.3,0.1