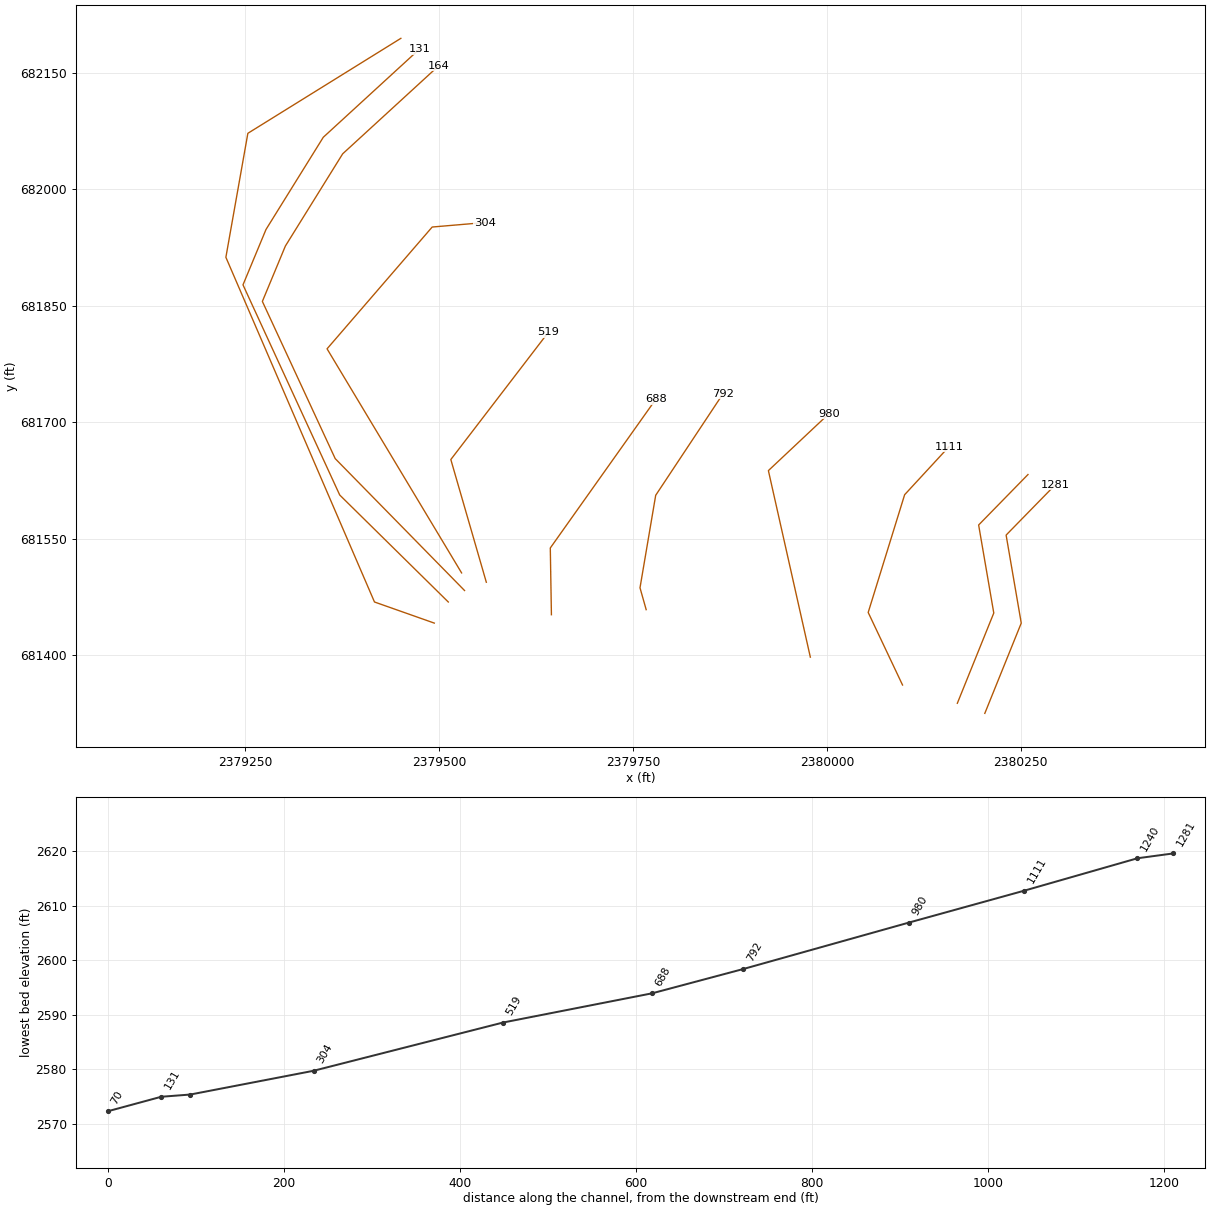
HEC-RAS study STNKGRN.prj: STNKGRN

--- STNKGRN.g01 (geometry) --- (continued)

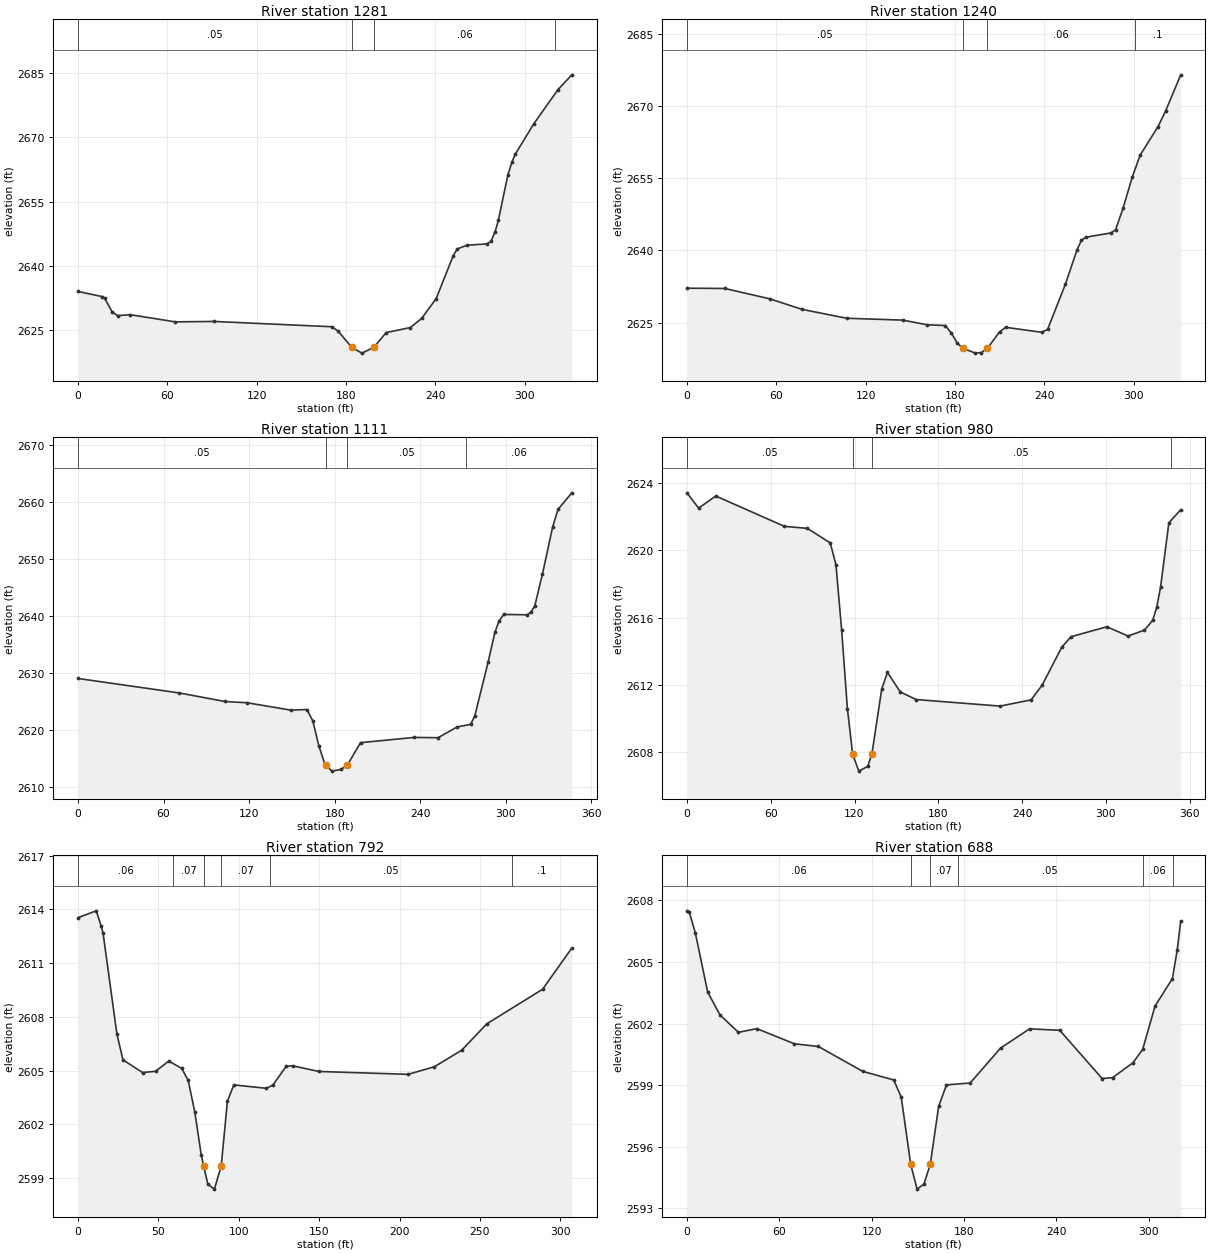
Type RM Length L Ch R = 1 ,1281    ,38.6,40.9,39.5
XS GIS Cut Line= 4
2380203.58732203681324.5998301732380250.56525881681440.960565905
2380231.05134661 681554.430351682380294.65224564681619.476725691
#Sta/Elev= 30
       0 2633.98    16.3 2632.77    17.9 2632.36    22.9  2629.2    26.5 2628.33
    35.1 2628.55    65.3 2626.87    91.2 2626.97   170.4 2625.73   174.4 2624.79
  183.912620.877   190.6 2619.56   198.52620.877   206.9 2624.36   223.1 2625.54
   230.7 2627.66   240.5 2632.31   251.8 2642.25   254.7 2643.95   261.2 2644.79
   274.5 2645.11   277.3 2645.69   280.1 2647.99   282.3 2650.68   288.6 2661.18
   291.4 2664.28   293.7 2666.13     306 2673.17   322.3 2681.19   331.6 2684.65
#Mann= 4, -1 ,  0
       0    0.05       0  183.91   0.045       0   198.5    0.06       0
  320.62     0.1       0
Bank Sta=183.91,198.5
XS Rating Curve= 0 ,0
Exp/Cntr(USF)=0,0
Exp/Cntr=0.3,0.1

Type RM Length L Ch R = 1 ,1240    ,132.5,128.4,124.8
XS GIS Cut Line= 4
2380168.17318507681337.6091049762380215.15112185681453.969840707
2380195.63720965681567.4396264822380259.23810868681632.486000494
#Sta/Elev= 30
       0 2632.15    25.4 2632.09    55.6 2629.94    77.2 2627.76   107.2 2625.91
     145 2625.52   161.2 2624.56   173.4  2624.4   177.4 2622.91   181.5 2620.76
  185.332619.673   193.7 2618.67   197.7  2618.8  201.772619.674   209.9 2623.08
     214 2624.03   238.2    2623   242.2  2623.6   254.2 2633.03     262 2640.16
   264.9 2642.08   267.7 2642.72   284.7 2643.62   287.8 2644.24   292.9 2648.77
     299 2655.17   304.3 2659.74   316.3 2665.67   321.4  2668.9   331.6 2676.44
#Mann= 4, -1 ,  0
       0    0.05       0  185.33   0.045       0  201.77    0.06       0
  300.62     0.1       0
Bank Sta=185.33,201.77
XS Rating Curve= 0 ,0
Exp/Cntr(USF)=0,0
Exp/Cntr=0.3,0.1

Type RM Length L Ch R = 1 ,1111    ,126.7,131.1,134.3
XS GIS Cut Line= 4
2380097.52293686681361.1698512282380053.25792431681454.692578196
 2380100.2358611681606.4674508892380157.28625759681668.260864925
#Sta/Elev= 30
       0 2629.01    70.8 2626.48   103.1 2624.97   118.6 2624.75   149.4 2623.45
   160.5 2623.56   164.7 2621.59   168.9 2617.22   173.1 2614.04  173.94 2613.76
   178.1 2612.74   184.5 2613.04  188.872613.762   198.2 2617.74   235.9 2618.66
   252.6 2618.61     266  2620.5   275.5 2620.96   278.4 2622.44   287.8 2631.93
   292.5  2637.1   295.4 2639.11   298.7 2640.26   315.3  2640.2     318 2640.73
   320.5 2641.76   325.9 2647.37     333 2655.58   336.8 2658.71   346.5 2661.62
#Mann= 4, -1 ,  0
       0    0.05       0  173.94   0.045       0  188.87    0.05       0
  272.35    0.06       0
Bank Sta=173.94,188.87
XS Rating Curve= 0 ,0
Exp/Cntr(USF)=0,0
Exp/Cntr=0.3,0.1

Type RM Length L Ch R = 1 ,980     ,191.7,188.2,186.5
XS GIS Cut Line= 3
2379978.68496772681397.0722136712379924.61065127681637.545162917
2380002.73372389681710.953765176
#Sta/Elev= 30
       0 2623.41     8.3  2622.5    20.6 2623.22    69.8 2621.42    86.2  2621.3
   102.6 2620.44   106.7 2619.14   110.8 2615.25   114.9  2610.6  118.692607.882
   123.1 2606.89   129.4 2607.17  132.432607.886   139.5 2611.76   143.6 2612.75
   152.8 2611.59   164.1 2611.14   224.3 2610.75   246.5 2611.12   254.4 2611.99
   268.5 2614.25   275.1 2614.87   300.8 2615.46     316 2614.91   327.7 2615.26
   333.6 2615.84   336.5 2616.61   339.3 2617.84   345.2 2621.63   353.7 2622.41
#Mann= 4, -1 ,  0
       0    0.05       0  118.69   0.045       0  132.43    0.05       0
  346.48    0.06       0
Bank Sta=118.69,132.43
XS Rating Curve= 0 ,0
Exp/Cntr(USF)=0,0
Exp/Cntr=0.3,0.1

Type RM Length L Ch R = 1 ,792     ,105.2,103.5,100.2
XS GIS Cut Line= 4
2379767.05387866681458.3062656412379759.10376628681486.493027713
2379779.34041598  681605.74471342379866.06891466681736.560198912
#Sta/Elev= 30
       0 2613.54    11.3 2613.92    14.4 2613.05    15.5  2612.7    24.1 2607.06
    27.9  2605.6    40.1 2604.89    48.2 2604.96    56.4 2605.53    64.5 2605.12
    68.5 2604.45    72.6 2602.69    76.6  2600.3   78.13 2599.68    80.7 2598.66
    84.8 2598.38   89.062599.676    92.9 2603.29    96.9  2604.2   117.2 2604.01
   121.3  2604.2   129.4 2605.23   133.4 2605.27   149.7 2604.95   205.3 2604.79
   221.6 2605.21   238.6 2606.13   254.3 2607.61     289 2609.54   307.2 2611.84
#Mann= 6, -1 ,  0
       0    0.06       0   59.29    0.07       0   78.13   0.045       0
   89.06    0.07       0  119.29    0.05       0  270.24     0.1       0
Bank Sta=78.13,89.06
XS Rating Curve= 0 ,0
Exp/Cntr(USF)=0,0
Exp/Cntr=0.3,0.1

Type RM Length L Ch R = 1 ,688     ,169.7,169.5,169.2
XS GIS Cut Line= 3
2379644.91124302 681451.801628242379643.46576804681537.807389433
2379779.34041598681729.332824022
#Sta/Elev= 30
       0 2607.49     1.4 2607.45     5.4 2606.42    13.4 2603.54    21.4 2602.42
    33.4 2601.57    45.4 2601.75    69.8 2601.01    85.4 2600.88   114.1 2599.67
   134.3 2599.25   139.2 2598.42  145.34 2595.14   149.5 2593.93   153.9 2594.17
  158.08 2595.14   163.5 2597.96   168.6 2599.01     184  2599.1   203.7  2600.8
   222.6 2601.74   242.2 2601.67   269.7 2599.32   276.5 2599.36   289.8 2600.09
   296.1 2600.74   304.1 2602.85   315.4 2604.19   318.5 2605.57   320.8 2606.99
#Mann= 6, -1 ,  0
       0    0.06       0  145.34   0.045       0  158.08    0.07       0
  176.02    0.05       0  296.02    0.06       0  316.02     0.1       0
Bank Sta=145.34,158.08
XS Rating Curve= 0 ,0
Exp/Cntr(USF)=0,0
Exp/Cntr=0.3,0.1

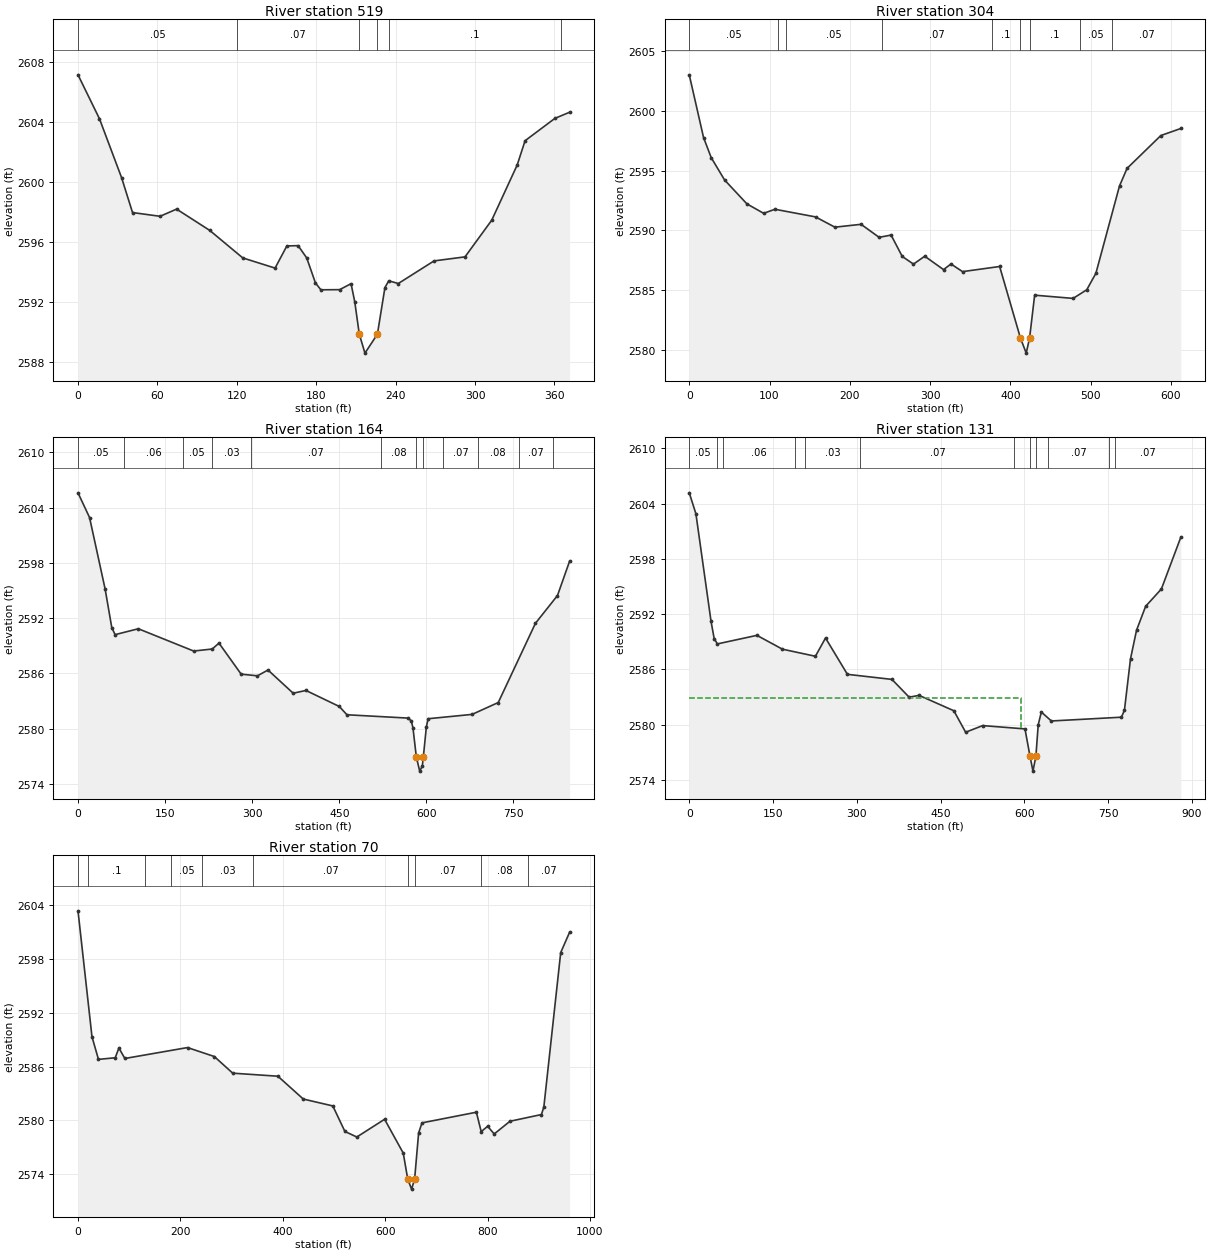
Type RM Length L Ch R = 1 ,519     ,216.2,215.2,215
XS GIS Cut Line= 3
2379561.00591104681493.618217693 2379515.2275196681651.817075362
2379640.98384269681815.878485368
#Sta/Elev= 30
       0 2607.16    16.2 2604.23    32.9  2600.3    41.2 2597.96      62 2597.71
    74.5 2598.19    99.5 2596.77   124.5 2594.93   148.9 2594.25   157.8 2595.73
   166.3 2595.75   172.8 2594.93   179.4 2593.26   183.5  2592.8   197.7 2592.81
   206.3 2593.21   209.1    2592  212.542589.834   216.8 2588.57  226.212589.834
   231.9 2592.95   234.8  2593.4     242 2593.22     269 2594.73   292.4    2595
   312.6 2597.45   331.8 2601.13   337.8 2602.76   360.3 2604.25   371.4 2604.66
#Mann= 6, -1 ,  0
       0    0.05       0     120    0.07       0  212.54   0.045       0
  226.21    0.07       0  234.69     0.1       0  364.69    0.05       0
Bank Sta=212.54,226.21
XS Rating Curve= 0 ,0
Exp/Cntr(USF)=0,0
Exp/Cntr=0.3,0.1

Type RM Length L Ch R = 1 ,304     ,138.8,140,140.7
XS GIS Cut Line= 4
 2379529.1189348681505.683424266 2379355.6968188681794.538301015
2379491.21916459681951.5458967472379558.98033749681957.330387116
#Sta/Elev= 30
       0 2603.02    17.8 2597.77    27.4 2596.08      44 2594.22    71.8 2592.22
    92.7 2591.43   106.7 2591.77   157.3 2591.13   181.4 2590.27     214 2590.51
   236.5 2589.42   251.4 2589.61   265.3 2587.82   279.3 2587.18   293.3 2587.84
   316.7 2586.72     326 2587.19   340.4 2586.55   386.6 2586.98  412.49    2581
   419.7 2579.73  423.912580.997   430.2 2584.58   478.1 2584.31   495.1 2585.03
   506.5 2586.41   535.9 2593.72   545.3 2595.19   587.4 2597.94   612.3 2598.53
#Mann= 9, -1 ,  0
       0    0.05       0     110    0.06       0     120    0.05       0
     240    0.07       0  376.92     0.1       0  412.49   0.045       0
  423.91     0.1       0  486.92    0.05       0  526.92    0.07       0
Bank Sta=412.49,423.91
XS Rating Curve= 0 ,0
Exp/Cntr(USF)=0,0
Exp/Cntr=0.3,0.1

Type RM Length L Ch R = 1 ,164     ,32.8,33,32.8
XS GIS Cut Line= 6
2379532.93274223681482.9605013662379366.20030086681652.998257192
2379272.30014614681855.6424780362379301.96730141 681927.04936379
2379375.80016252682045.884381199 2379499.5612571682159.342325025
#Sta/Elev= 30
       0  2605.6    19.9 2602.92    46.8 2595.13    58.2 2590.96    63.9  2590.2
   103.9 2590.84   199.2 2588.42   231.2 2588.64   242.8 2589.28     281 2585.91
   309.1 2585.73   327.2 2586.36   370.6 2583.84   392.6 2584.14     450  2582.4
   463.2  2581.5   568.2 2581.14     574 2580.84   576.9 2580.07   582.7 2576.92
   588.5 2575.38     593 2575.93  594.782576.937     600  2580.2     603 2581.07
   678.7 2581.54   723.8 2582.83   787.8 2591.43   825.8 2594.45   846.6 2598.17
#Mann= 12, -1 ,  0
       0    0.05       0      80    0.06       0     180    0.05       0
     230    0.03       0  298.14    0.07       0  521.49    0.08       0
   582.7   0.045       0  594.78    0.08       0  628.48    0.07       0
  688.73    0.08       0  758.73    0.07       0  818.73    0.05       0
Bank Sta=582.7,594.78
XS Rating Curve= 0 ,0
Exp/Cntr(USF)=0,0
Exp/Cntr=0.3,0.1

Type RM Length L Ch R = 1 ,131     ,58.5,60.6,62.6
XS GIS Cut Line= 6
2379511.97435465681468.1737304852379372.01584013 681606.08277409
2379247.32566953681877.000508403 2379276.9928248681948.407394157
2379350.82568591682067.2424115662379474.58678049682180.700355393
#Sta/Elev= 30
       0 2605.16    11.9 2602.89      39 2591.21    44.6 2589.35    50.3 2588.77
   121.1  2589.7   166.7  2588.2   225.8 2587.43   243.9 2589.41   283.1 2585.47
   362.8 2584.92   393.6 2582.99   411.3 2583.19   473.6 2581.52   494.7 2579.19
   525.2 2579.91   600.9 2579.55  609.932576.583   615.2 2574.97  620.462576.583
   624.6 2579.99   630.2 2581.38   648.2 2580.41   773.5 2580.82   778.9 2581.56
   789.8 2587.15   800.6 2590.25   816.9 2592.85   845.1 2594.73   879.9 2600.35
#Mann= 12, -1 ,  0
       0    0.05       0      50     0.1       0      60    0.06       0
     190    0.05       0  206.49    0.03       0  306.49    0.07       0
  582.05    0.08       0  609.93   0.045       0  620.46    0.08       0
  641.72    0.07       0  751.96    0.08       0  761.96    0.07       0
#XS Ineff= 2 , 0
          593.36  2582.9
Permanent Ineff=
       F       F
Bank Sta=609.93,620.46
XS Rating Curve= 0 ,0
Exp/Cntr(USF)=0,0
Exp/Cntr=0.3,0.1

Type RM Length L Ch R = 1 ,70      ,,,
XS GIS Cut Line= 5
2379493.91927356681440.9725209832379416.83807719681468.177649115
2379225.26863326681912.5280752712379253.60730839682072.358203046
2379450.84448735 682194.78127964
#Sta/Elev= 30
       0  2603.4    27.3 2589.34      40 2586.81    72.7 2586.99    79.9 2588.08
    91.5 2586.91   213.9 2588.13   266.2 2587.13   302.2 2585.27   390.4 2584.93
     440 2582.38   497.7 2581.61   521.3 2578.76   544.6 2578.14   598.8 2580.12
   635.3 2576.34  644.05 2573.43   651.5 2572.32  657.46 2573.43   665.3  2578.6
   671.9 2579.72   778.1 2580.91   787.5 2578.74   800.1 2579.34   812.9 2578.48
   843.7  2579.9   905.2 2580.65   909.9 2581.51   942.8 2598.74   960.1    2601
#Mann= 10, -1 ,  0
       0    0.05       0      20     0.1       0  131.74    0.06       0
  181.74    0.05       0  241.74    0.03       0  341.74    0.07       0
  644.05   0.045       0  657.46    0.07       0  787.95    0.08       0
  877.95    0.07       0
Bank Sta=644.05,657.46
XS Rating Curve= 0 ,0
Exp/Cntr(USF)=0,0
Exp/Cntr=0.3,0.1
LCMann Table=0

Chan Stop Cuts=-1
Use User Specified Reach Order=0
Composite Channel Slope=5